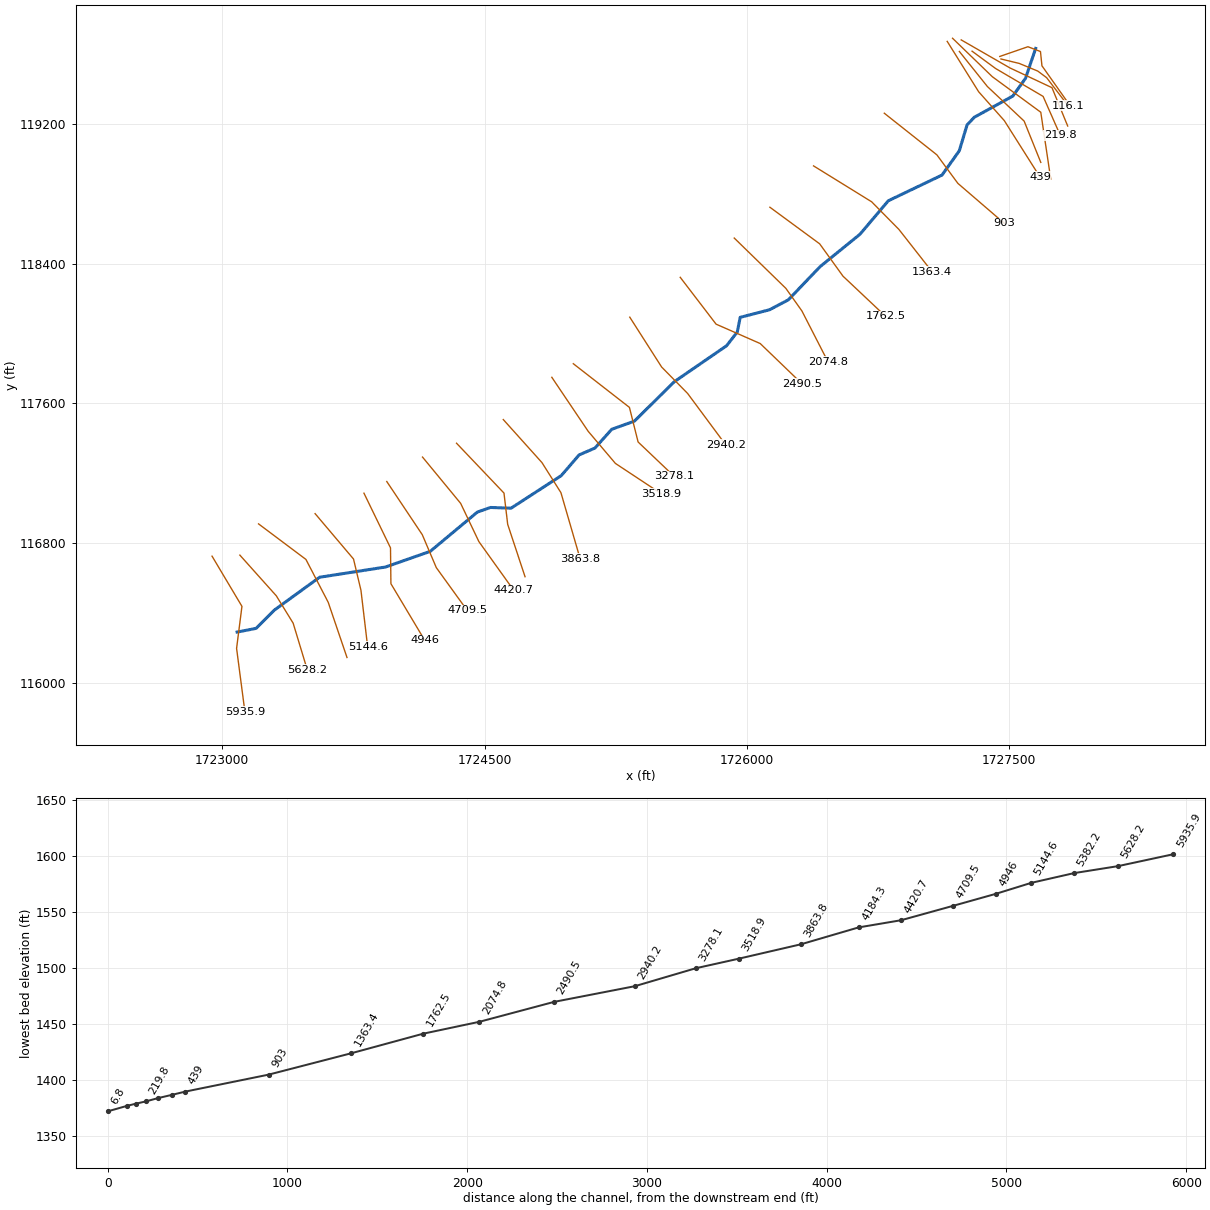
--- Wolfpen Branch A.prj (project) ---

Proj Title=Wolfpen Branch A
Current Plan=p01
Default Exp/Contr=0,0
English Units
Geom File=g01
Flow File=f01
Plan File=p01
BEGIN DESCRIPTION:
END DESCRIPTION:
DSS Export Rating Curves= 0
DSS Export Rating Curve Sorted= 0
DSS Export Volume Flow Curves= 0
DXF OffsetX= 0
DXF OffsetY= 0
DXF ScaleX= 0
DXF ScaleY= 0

--- Wolfpen Branch A.p01 (plan) ---

Plan Title=Floodplain
Program Version=4.00
Geom File=g01
Flow File=f01
K Sum by GR=0
Std Step Tol=0.01
Critical Tol=0.01
Num of Std Step Trials=20
Max Error Tol=0.3
Flow Tol Ratio=0.001
Split Flow NTrial=30
Split Flow Tol=0.02
Split Flow Ratio=0.02
Log Output Level=0
Friction Slope Method=1
Unsteady Friction Slope Method=2
Unsteady Bridges Friction Slope Method=1
Global Log Level=0
CheckData=False
Run HTab=0
Run UNet=0
Run PostProcess=0
UNET Theta=0
UNET Theta Warmup=0
UNET ZTol=0
UNET ZSATol=0
UNET MxIter=0
UNET MaxInSteps=0
UNET DtIC=0
UNET DtMin=0
UNET MaxCRTS=0
UNET WFStab=0
UNET SFStab=0
UNET WFX=0
UNET SFX=0
UNET DSS MLevel=0
UNET DZMax Abort=0
UNET Convert EG Bridges=0
UNET Use Existing IB Tables=0
UNET Froude Limit=0
UNET Froude Power=0
Write IC File=0
Echo Input=False
Echo Output=False
Write Detailed=0

--- Wolfpen Branch A.f01 (steady flow) ---

Flow Title=NFF Regression Equation
Program Version=4.00
Number of Profiles=1
Profile Names=P100yr
River Rch & RM=Wolfpen Branch A,Main      ,5935.9
555.9483
River Rch & RM=Wolfpen Branch A,Main      ,4946
573.4762
River Rch & RM=Wolfpen Branch A,Main      ,3863.8
630.8202
River Rch & RM=Wolfpen Branch A,Main      ,2074.8
695.7909
River Rch & RM=Wolfpen Branch A,Main      ,286.4
763.3717
Boundary for River Rch & Prof#=Wolfpen Branch A,Main      ,1
Up Type=0
Dn Type=3
Dn Slope=0.040553

--- Wolfpen Branch A.g01 (geometry) ---

Geom Title=USGS 10m DEM
Program Version=4.00

River Reach=Wolfpen Branch A,Main
Reach XY= 30
     1723085.055      116290.216     1723193.573      116311.214
     1723298.047      116416.144     1723556.552      116604.147
     1723933.677      116662.727     1724189.442      116752.443
     1724459.112      116977.567     1724533.874      117003.892
     1724651.478      116999.697     1724938.216      117186.057
      1725041.13      117305.108      1725131.08      117344.005
     1725227.512      117451.783     1725356.722      117498.248
     1725585.072      117724.194      1725883.93       117930.11
      1725945.49       118009.31     1725961.649       118092.76
     1726129.949      118136.435     1726236.916      118192.958
     1726418.639      118383.189     1726646.552      118568.559
     1726808.827      118760.614      1727115.75      118907.694
     1727214.817      119046.873     1727259.184      119195.169
     1727300.504      119238.984     1727520.693      119360.248
     1727593.457       119461.98     1727651.496      119633.245

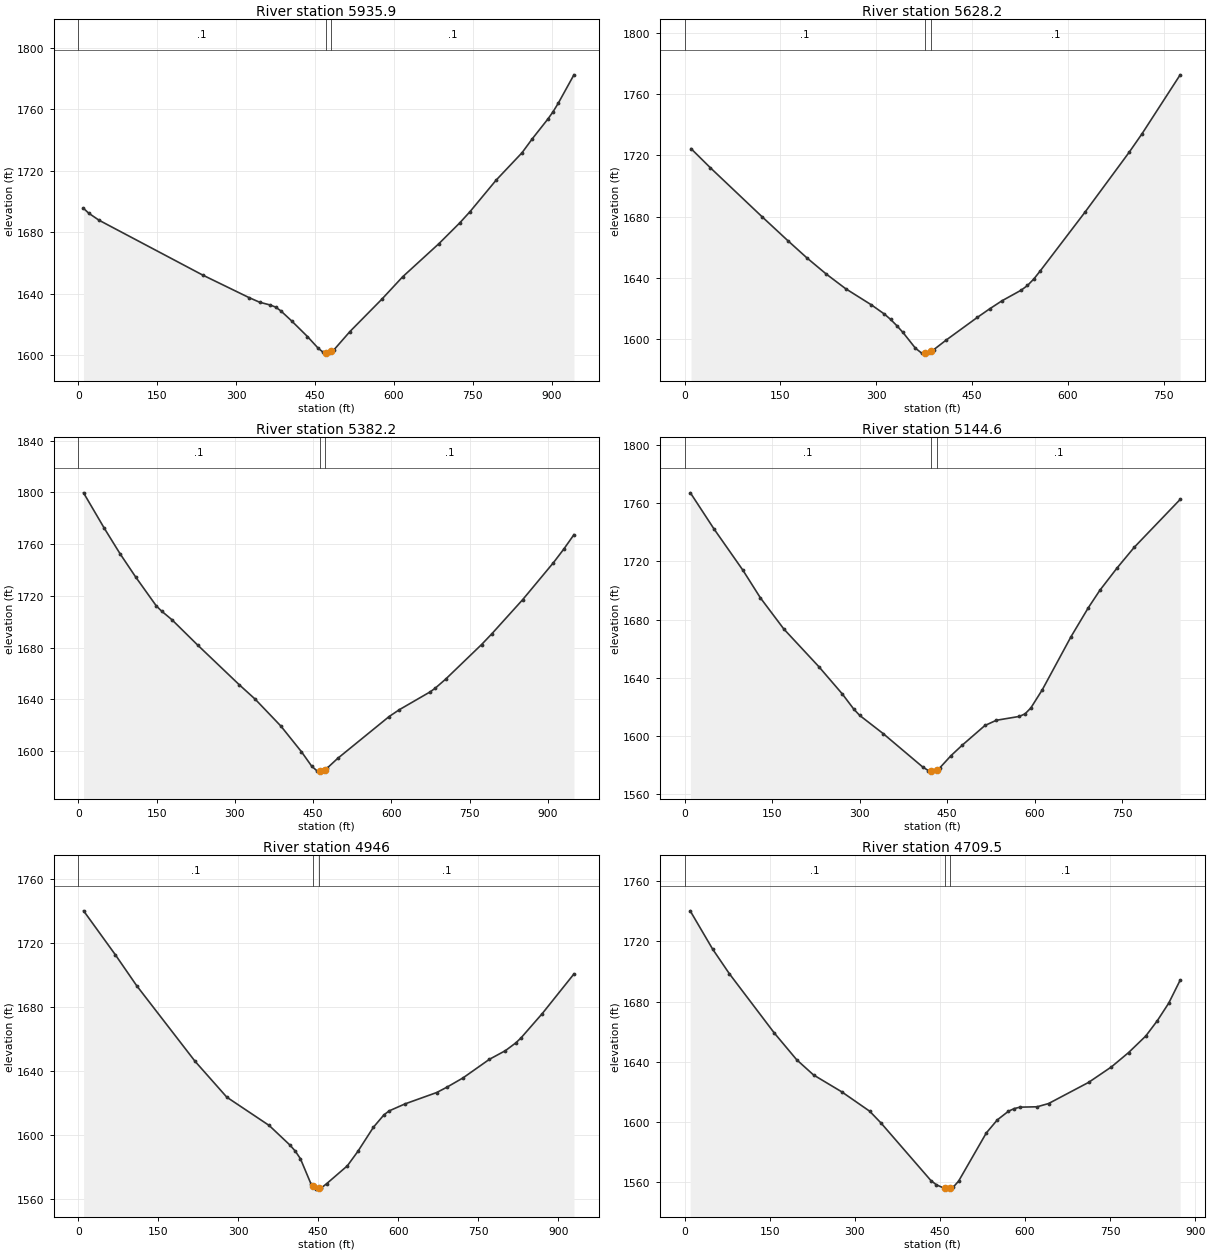
Type RM Length L Ch R = 1 ,5935.9  ,293.7,307.6,321.8
XS GIS Cut Line= 4
     1722941.576      116725.037     1723112.618      116437.382
      1723081.94      116196.683     1723129.357      115834.622
#Sta/Elev= 30
     9.8  1695.6    19.7 1692.42    39.4 1687.83   236.2 1652.24   324.8 1637.51
   344.8 1634.52     365 1632.71   375.1 1631.38   385.2 1628.88   405.4 1622.46
   435.8 1612.19     456 1604.68   466.1 1601.85   471.2 1601.64   476.2 1601.43
   481.2 1602.53   486.3 1603.65   516.6 1615.49   577.3 1636.53   616.8 1651.06
   685.9 1672.66   725.3 1686.08   745.1  1693.5   794.4 1713.84   843.8 1731.71
   863.5 1740.87   893.1 1753.68     903 1758.46   912.9 1764.03   942.5 1782.36
#Mann= 3 , 0 , 0
       0      .1       0   471.2    .045       0   481.2      .1       0
Bank Sta=471.2,481.2
XS Rating Curve= 0 ,0
Exp/Cntr=0.3,0.1

Type RM Length L Ch R = 1 ,5628.2  ,247.5,246,244.5
XS GIS Cut Line= 4
     1723100.664      116730.957     1723309.105      116497.861
     1723405.481       116340.97     1723486.168      116074.255
#Sta/Elev= 30
    10.1 1724.47    40.3 1711.99     121 1680.05   161.4 1664.39   191.7 1652.95
   221.9 1642.42   252.2 1632.87   292.5  1622.3   312.7 1616.32   322.4 1612.83
   332.1 1608.76   341.8 1604.28   361.2 1594.04   370.8 1590.86   375.5 1590.83
   380.5 1590.79   385.5    1592   390.2 1593.14   409.6  1599.4   458.1 1614.14
   477.4 1619.74   496.8 1625.03   526.7 1631.93   536.6    1635   546.6  1639.3
   556.5  1644.5   626.2 1682.72   695.9 1722.21   715.8 1734.17   775.5  1772.7
#Mann= 3 , 0 , 0
       0      .1       0   375.5    .045       0   385.5      .1       0
Bank Sta=375.5,385.5
XS Rating Curve= 0 ,0
Exp/Cntr=0.3,0.1

Type RM Length L Ch R = 1 ,5382.2  ,242.7,237.6,232.5
XS GIS Cut Line= 4
     1723207.557      116909.815     1723478.386      116706.399
     1723605.815       116460.98     1723713.359      116144.369
#Sta/Elev= 30
      10 1799.63    49.8 1772.23    79.7 1752.72   109.6 1734.74   149.4 1712.23
   159.4 1708.27   179.3 1701.56   229.1 1681.78   308.8 1651.11   338.7 1640.19
   388.1 1619.34   427.6 1599.45   447.4 1588.19   457.2 1584.78   462.1 1584.64
   467.1 1584.51   472.1 1585.73     477 1586.92   496.7 1594.28   595.5  1626.7
   615.2 1632.03   674.3 1645.82   684.1 1648.72   703.8 1655.61   772.6 1682.34
   792.3 1690.67   851.3 1717.01   910.3 1745.64     930 1756.05   949.6 1767.28
#Mann= 3 , 0 , 0
       0      .1       0   462.1    .045       0   472.1      .1       0
Bank Sta=462.1,472.1
XS Rating Curve= 0 ,0
Exp/Cntr=0.3,0.1

Type RM Length L Ch R = 1 ,5144.6  ,203.2,198.6,194
XS GIS Cut Line= 4
     1723530.994      116968.535     1723750.642      116708.544
     1723793.227      116529.239     1723831.329      116206.491
#Sta/Elev= 30
      10 1767.14    50.1 1742.54   100.1 1713.89   130.1 1694.89   170.2 1673.51
   230.2 1647.64   270.3 1628.93   290.3 1618.35   300.3 1614.11   340.4 1601.64
   408.3 1578.65     418 1576.19   422.6 1576.01   427.7 1575.82   432.6 1576.91
   437.3 1577.96   456.7 1586.44   476.1  1593.7   514.9 1607.19   534.5 1610.78
   573.9 1613.43   583.7  1615.2   593.6 1619.25   613.3 1631.79   662.5 1668.25
   692.1 1688.12   711.8 1700.07   741.3 1715.42   770.8 1729.66   849.6 1762.61
#Mann= 3 , 0 , 0
       0      .1       0   422.6    .045       0   432.6      .1       0
Bank Sta=422.6,432.6
XS Rating Curve= 0 ,0
Exp/Cntr=0.3,0.1

Type RM Length L Ch R = 1 ,4946    ,228.6,236.5,244.5
XS GIS Cut Line= 4
      1723810.32      117085.809     1723962.144      116772.473
     1723964.504      116567.171     1724157.108      116244.175
#Sta/Elev= 30
     9.9 1740.11    69.6 1712.54   109.4 1693.29   218.9 1645.96   278.5 1623.49
     358 1605.77   397.1 1593.46   406.8 1589.79   416.6 1584.96   436.2 1569.35
     441 1567.66   445.9 1565.94     451 1566.34   455.7 1566.71   465.5 1569.27
   504.6 1580.53   524.2  1589.5   553.5 1604.67   573.3 1612.45   583.2 1614.93
   612.9  1619.3   672.3 1626.41     692 1629.86   721.7 1635.58   771.2 1647.22
   800.9 1652.57   820.7 1657.49   830.6 1660.68   870.2 1675.81   929.6  1700.6
#Mann= 3 , 0 , 0
       0      .1       0     441    .045       0     451      .1       0
Bank Sta=441,451
XS Rating Curve= 0 ,0
Exp/Cntr=0.3,0.1

Type RM Length L Ch R = 1 ,4709.5  ,288,288.8,289.5
XS GIS Cut Line= 4
     1723940.906        117152.4     1724143.848      116847.986
     1724224.081      116659.203     1724401.066      116413.784
#Sta/Elev= 30
     9.9 1740.29    49.4  1714.9    79.1 1698.42   158.2 1659.06   197.8 1641.23
   227.4 1631.17   276.9    1620   326.3 1607.08   346.1 1599.32   434.2    1561
     444 1558.15   458.5 1555.74   463.5 1555.28   468.5 1555.89   473.3 1556.48
   483.1 1560.63   531.9 1592.63   551.4 1601.35     571 1607.08   581.1 1608.82
   591.2 1609.77   621.4 1610.02   641.6 1612.17   712.2 1626.24   752.5 1636.56
   782.8  1646.1     813 1657.08   833.2 1667.18   853.4  1678.9   873.6  1694.2
#Mann= 3 , 0 , 0
       0      .1       0   458.5    .045       0   468.5      .1       0
Bank Sta=458.5,468.5
XS Rating Curve= 0 ,0
Exp/Cntr=0.3,0.1

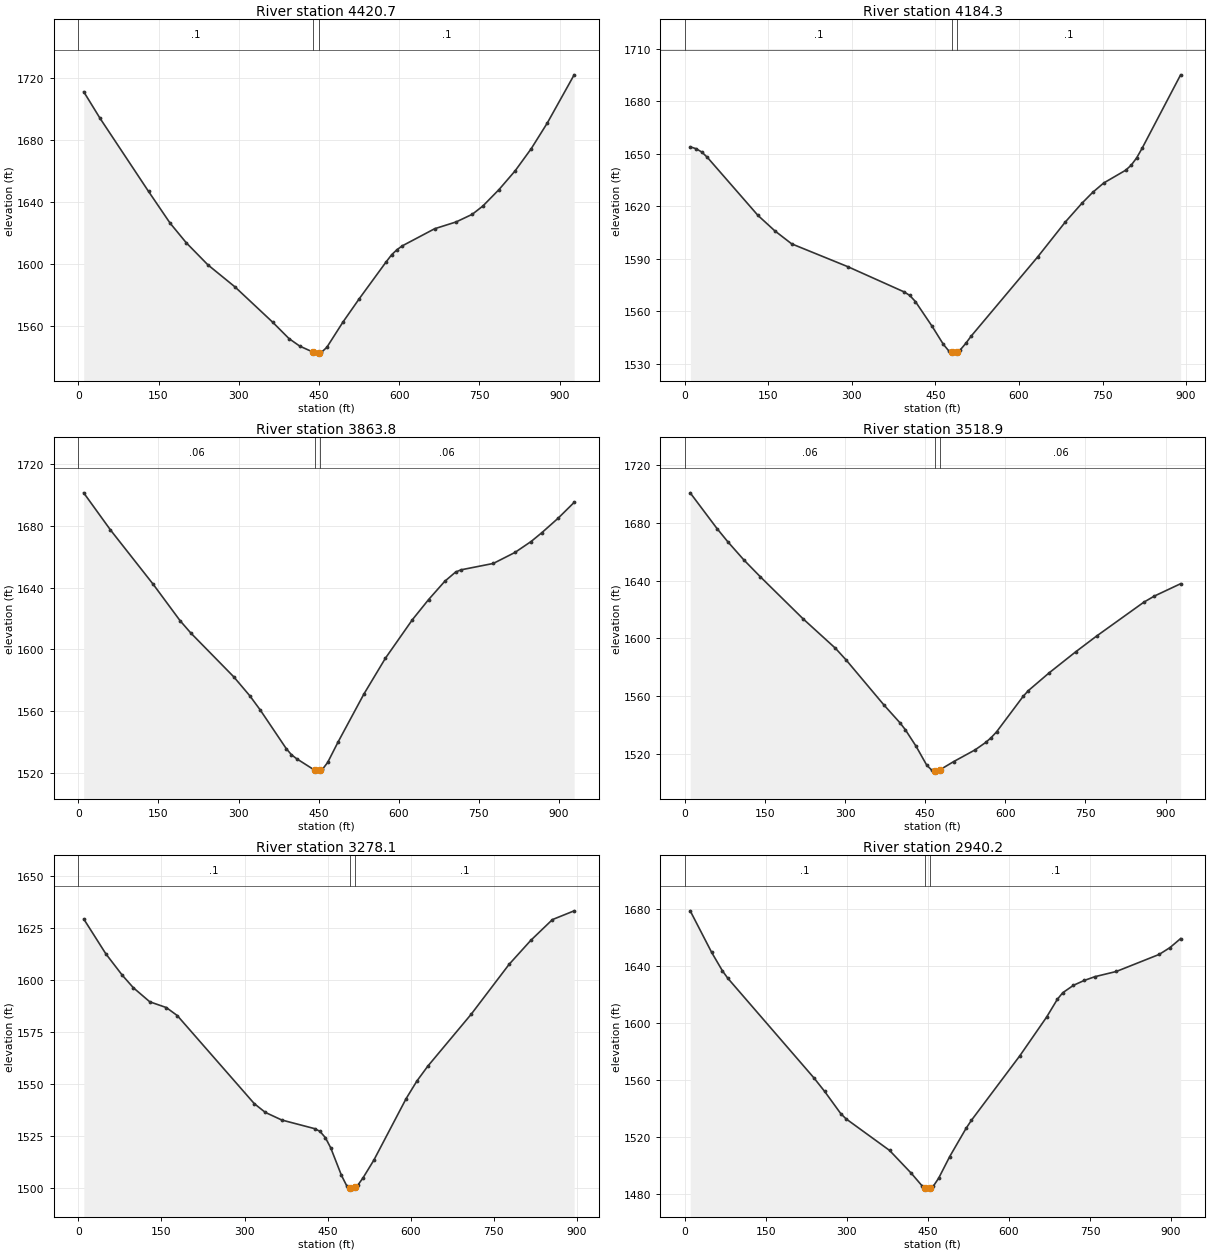
Type RM Length L Ch R = 1 ,4420.7  ,243,236.4,229.9
XS GIS Cut Line= 4
     1724145.227      117292.476     1724363.309      117027.331
     1724467.608      116808.204     1724665.844      116530.672
#Sta/Elev= 30
    10.1 1710.87    40.4 1693.87   131.3 1646.64   171.7 1626.16   201.9 1613.53
   242.3 1599.32   292.8 1585.16   363.5 1562.34   393.9 1551.82   414.1 1546.95
   439.4 1543.03   444.4 1542.45   449.4 1542.69   454.5 1542.94   464.7 1546.22
     495 1562.58   525.3 1577.52   575.9 1601.41     586  1605.9     596 1609.16
   606.1 1611.64   666.2  1622.6   706.4 1626.99   736.5 1631.89   756.5 1637.28
   786.6 1647.85   816.7  1659.9   846.8 1674.18   876.9 1690.75   927.1 1721.78
#Mann= 3 , 0 , 0
       0      .1       0   439.4    .045       0   449.4      .1       0
Bank Sta=439.4,449.4
XS Rating Curve= 0 ,0
Exp/Cntr=0.3,0.1

Type RM Length L Ch R = 1 ,4184.3  ,311.2,320.5,329.8
XS GIS Cut Line= 4
     1724339.711      117371.861     1724611.088      117086.326
     1724632.326      116906.981     1724731.437      116607.287
#Sta/Elev= 30
    10.1 1653.96    20.2 1652.92    30.3 1651.05    40.4 1648.01   131.3 1614.79
   161.6 1605.96   191.9 1598.51   292.9 1585.43   393.9 1571.02     404 1568.99
     414 1565.54   444.1 1551.34   464.2 1541.06   474.2 1537.22   479.2 1536.62
   484.2 1536.03   489.2 1536.89   494.3 1537.77   504.3 1541.55   514.3 1545.82
   633.7  1591.1     683 1610.94   712.6 1621.59   732.3 1627.95   752.1 1633.31
   791.5 1640.61   801.4 1643.47   811.3 1647.69   821.1  1653.2   890.2 1695.16
#Mann= 3 , 0 , 0
       0      .1       0   479.2    .045       0   489.2      .1       0
Bank Sta=479.2,489.2
XS Rating Curve= 0 ,0
Exp/Cntr=0.3,0.1

Type RM Length L Ch R = 1 ,3863.8  ,342,344.9,347.7
XS GIS Cut Line= 4
     1724607.108      117507.438     1724828.189       117260.95
     1724936.739      117088.685      1725046.47      116710.472
#Sta/Elev= 30
      10 1701.43    60.2 1677.35   140.5 1641.99   190.6  1618.5   210.7 1610.51
     291 1582.14   321.1 1569.83   340.8 1560.55   389.3 1535.59     399 1531.63
   408.7 1529.04   442.5  1521.6   447.5 1520.97   452.5 1521.59   457.2 1522.18
   466.9 1526.59   486.2 1539.73   534.7 1570.92   575.1 1594.21   625.6 1619.18
   655.9 1632.21   686.2 1644.07   706.4 1650.02   716.5 1651.49   777.1 1655.64
   817.5 1662.74   847.8 1669.85   867.9 1675.56   898.2 1684.88   928.5 1695.24
#Mann= 3 , 0 , 0
       0     .06       0   442.5    .045       0   452.5     .06       0
Bank Sta=442.5,452.5
XS Rating Curve= 0 ,0
Exp/Cntr=0.3,0.1

Type RM Length L Ch R = 1 ,3518.9  ,250.2,240.8,231.5
XS GIS Cut Line= 4
     1724884.659      117749.403     1725092.486      117440.295
     1725248.232      117256.231     1725510.424       117082.62
#Sta/Elev= 30
    10.1 1700.69    60.4 1675.93    80.5 1666.84   110.7 1654.22   140.9 1642.79
   221.5 1613.49   281.9 1593.17     302 1585.05   372.5 1554.02   402.6 1541.65
   412.7 1536.86   432.8 1525.41   452.8  1512.3   462.9 1508.58   467.9 1508.36
   472.9 1508.14   477.9 1509.12   503.1  1514.7   543.3 1522.83   563.4 1528.02
   573.4  1531.3   583.5 1535.27   633.2 1559.81   643.1 1563.86   682.4 1576.25
   731.5 1590.63   770.8 1601.59   859.3 1625.04   878.9 1629.25   928.1 1637.81
#Mann= 3 , 0 , 0
       0     .06       0   467.9    .045       0   477.9     .06       0
Bank Sta=467.9,477.9
XS Rating Curve= 0 ,0
Exp/Cntr=0.3,0.1

Type RM Length L Ch R = 1 ,3278.1  ,327.2,337.9,348.6
XS GIS Cut Line= 4
     1725007.533      117827.301     1725328.465      117577.163
     1725378.021       117378.94     1725583.323      117183.077
#Sta/Elev= 30
     9.9 1629.32    49.6 1612.66    79.4 1602.33    99.2 1596.36     129 1589.57
   158.8 1586.81   178.6 1582.96   317.6 1540.63   337.4 1536.44   367.2 1532.76
   426.4 1528.62   436.1 1527.32   445.8 1524.32   455.5 1519.43     475 1506.13
   484.7 1501.01   489.5 1500.29   494.5 1499.54   499.5 1500.46   504.2 1501.33
   513.9 1504.96   533.4 1513.46   591.8 1543.09   611.2 1551.53   630.8 1558.64
   709.1 1583.59   777.6 1607.59   816.7  1619.1   855.8 1629.09     895  1633.3
#Mann= 3 , 0 , 0
       0      .1       0   489.5    .045       0   499.5      .1       0
Bank Sta=489.5,499.5
XS Rating Curve= 0 ,0
Exp/Cntr=0.3,0.1

Type RM Length L Ch R = 1 ,2940.2  ,442.1,449.7,457.3
XS GIS Cut Line= 4
      1725330.49      118093.794     1725512.529      117808.423
     1725661.277      117656.842     1725879.496      117362.024
#Sta/Elev= 30
      10 1678.54    49.8 1649.35    69.7 1636.47    79.6  1631.3   238.9 1561.53
   258.8 1552.03   288.7 1536.44   298.7 1532.73   378.9  1510.7   419.4 1494.59
   439.6 1485.65   444.7 1484.59   449.7 1483.55   454.7 1484.52   459.8 1485.52
     470 1491.31   490.2 1506.29   520.5 1526.08   530.6 1531.83   620.3 1577.09
   669.8 1604.17   689.6  1616.6   699.6 1621.18   719.4 1626.37   739.2 1629.74
     759  1632.4   798.7 1636.05     878    1648   897.8 1652.73   917.7  1659.1
#Mann= 3 , 0 , 0
       0      .1       0   444.7    .045       0   454.7      .1       0
Bank Sta=444.7,454.7
XS Rating Curve= 0 ,0
Exp/Cntr=0.3,0.1

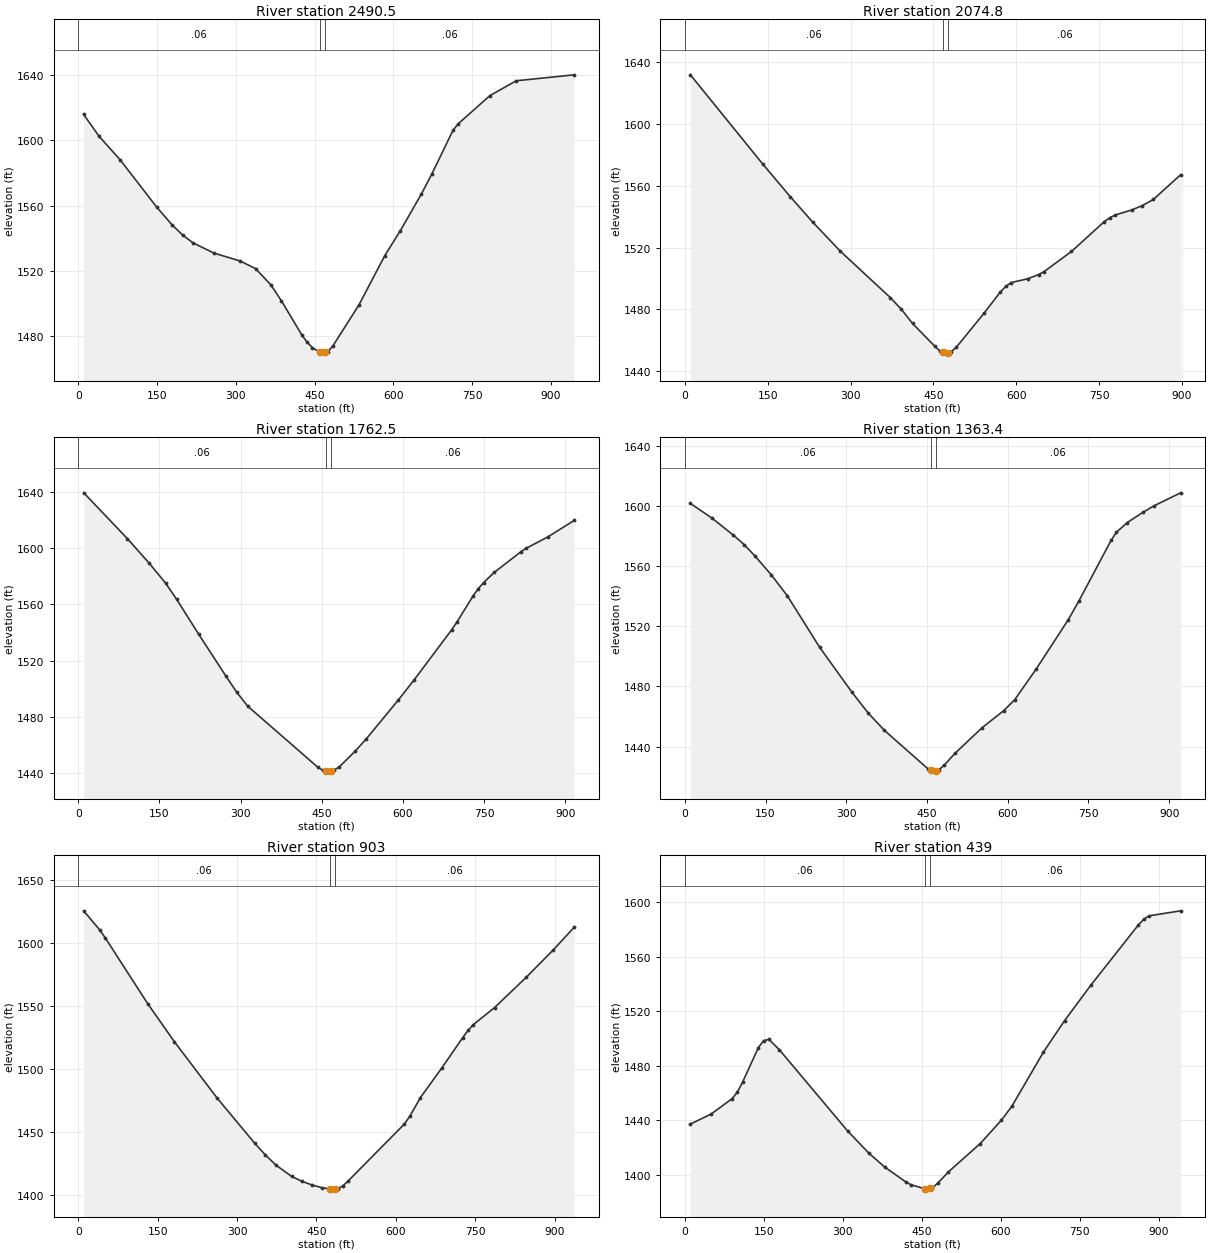
Type RM Length L Ch R = 1 ,2490.5  ,428.2,415.7,402.2
XS GIS Cut Line= 4
     1725618.978      118322.164     1725824.022      118053.842
     1726076.463      117942.786     1726314.804      117712.841
#Sta/Elev= 30
     9.9 1615.91    39.7 1602.35    79.5 1588.06     149 1559.14   178.8 1548.09
   198.6 1541.94   218.5 1537.12   258.2 1530.84   307.9 1526.02   337.7 1521.32
   367.2 1511.22   386.9 1501.61   426.3  1480.4   436.2 1476.11     446  1472.8
   460.7 1470.04   465.7 1469.52   470.7 1469.99   475.6 1470.45   485.4 1474.14
   534.7 1499.08   583.9 1529.29   613.5 1544.54   653.6 1567.06   673.7 1579.38
   713.8 1606.08   723.9  1610.1   784.1 1627.34   834.3 1636.44   944.7 1640.09
#Mann= 3 , 0 , 0
       0     .06       0   460.7    .045       0   470.7     .06       0
Bank Sta=460.7,470.7
XS Rating Curve= 0 ,0
Exp/Cntr=0.3,0.1

Type RM Length L Ch R = 1 ,2074.8  ,312.1,312.3,312.4
XS GIS Cut Line= 4
     1725927.853      118547.039     1726222.828      118259.144
      1726314.86      118129.355     1726463.527        117839.1
#Sta/Elev= 30
    10.1 1631.64   140.7 1574.13     191 1552.81   231.2 1536.55   281.5  1517.6
     372 1487.62   392.1    1480   412.2  1470.9     452 1456.33   461.9 1453.07
   466.8 1452.41   471.8 1451.73   476.8 1452.12   481.8  1452.5   491.7 1455.64
   541.5 1477.48   571.3 1491.34   581.2 1494.95   591.1 1497.36   620.7 1499.83
   640.5 1502.51   650.3 1504.43   699.8 1517.43   759.1  1536.7   768.9 1539.21
   778.8 1540.99   808.5 1544.23   828.2 1547.14     848 1551.05   897.4 1567.07
#Mann= 3 , 0 , 0
       0     .06       0   466.8    .045       0   476.8     .06       0
Bank Sta=466.8,476.8
XS Rating Curve= 0 ,0
Exp/Cntr=0.3,0.1

Type RM Length L Ch R = 1 ,1762.5  ,396.1,399.1,402.2
XS GIS Cut Line= 4
     1726131.684      118723.612     1726416.331      118514.002
     1726549.674      118328.843     1726793.265      118098.784
#Sta/Elev= 30
    10.1 1639.57    90.9 1606.81   131.3 1589.28   161.6 1575.03   181.8 1563.62
   222.2 1538.92   272.7 1508.99   292.9 1497.37   313.1 1487.46   442.8 1443.87
   452.7 1441.57   457.6 1441.35   462.6 1441.11   467.6 1441.46   472.5 1441.79
   482.5 1444.17   512.2  1455.5   532.1 1463.99   591.5 1491.77   621.1 1506.32
   690.1 1541.82   699.9 1547.37   729.5 1565.86   739.3 1571.15   749.2 1575.53
   768.9  1582.8   818.2 1597.54     828 1600.04   867.5 1608.01   916.7 1619.85
#Mann= 3 , 0 , 0
       0     .06       0   457.6    .045       0   467.6     .06       0
Bank Sta=457.6,467.6
XS Rating Curve= 0 ,0
Exp/Cntr=0.3,0.1

Type RM Length L Ch R = 1 ,1363.4  ,463.5,460.4,457.5
XS GIS Cut Line= 4
     1726381.283      118960.464     1726713.665      118754.701
     1726869.412      118596.595     1727059.553      118353.786
#Sta/Elev= 30
      10  1601.8    50.1 1592.07    90.2 1580.64   110.3 1574.34   130.3 1566.78
   160.4 1554.36   190.4 1540.33   250.6 1506.01   310.7  1476.1   340.8 1462.28
   370.9 1450.79   451.4 1425.33   456.5 1424.49   461.5 1423.68   466.5 1424.06
   471.6 1424.45   481.7 1427.54   501.9 1435.48   552.3 1452.53   592.7 1463.95
   612.9 1471.15   652.6 1491.44   712.3 1524.27   732.2 1536.84   791.9 1577.08
   801.9 1582.51   821.8 1588.91   851.6  1595.9   871.5 1600.08   921.2 1608.77
#Mann= 3 , 0 , 0
       0     .06       0   456.5    .045       0   466.5     .06       0
Bank Sta=456.5,466.5
XS Rating Curve= 0 ,0
Exp/Cntr=0.3,0.1

Type RM Length L Ch R = 1 ,903     ,461.9,464,466
XS GIS Cut Line= 4
     1726785.874      119262.093     1727086.513      119023.717
     1727206.507       118860.48     1727472.085      118631.535
#Sta/Elev= 30
    10.1 1625.77    40.4 1610.59    50.5 1604.52   131.3 1551.83   181.7 1521.61
   262.5 1476.81   333.2 1441.06   353.4 1431.71   373.6 1423.58     403 1414.68
   422.3 1410.81   441.6 1407.85   460.9 1405.63   475.1 1404.78   480.1 1404.55
   485.1 1404.69   489.8 1404.81   499.4 1406.97   509.1  1410.7   616.3 1456.39
   626.3 1462.44   646.4  1477.3   686.5 1500.67   726.5 1525.06   736.5  1530.7
   746.6 1535.39   786.6 1548.88   846.7 1573.09   896.8 1594.42   936.9 1612.66
#Mann= 3 , 0 , 0
       0     .06       0   475.1    .045       0   485.1     .06       0
Bank Sta=475.1,485.1
XS Rating Curve= 0 ,0
Exp/Cntr=0.3,0.1

Type RM Length L Ch R = 1 ,439     ,70.3,72,73.7
XS GIS Cut Line= 4
     1727145.732      119673.538      1727325.26      119385.404
       1727472.3      119219.593     1727675.707      118897.702
#Sta/Elev= 30
      10 1437.07    49.9 1444.51    89.9 1455.88    99.8 1460.61   109.8    1468
   139.8 1493.41   149.8  1498.5   159.8 1499.44   179.7 1491.76   309.5 1432.04
   349.6 1415.83   379.8  1405.6   420.1  1394.6   430.1 1392.54   455.4 1389.75
   460.4 1389.38   465.4  1389.9   470.4 1390.41   480.5 1393.69   500.7 1402.01
   561.1 1422.82   601.2 1439.91   621.2 1450.22   681.3 1490.08   721.4 1513.17
   771.5 1539.32   861.7 1583.53   871.7 1587.57   881.8 1590.21   941.9 1593.88
#Mann= 3 , 0 , 0
       0     .06       0   455.4    .045       0   465.4     .06       0
Bank Sta=455.4,465.4
XS Rating Curve= 0 ,0
Exp/Cntr=0.3,0.1

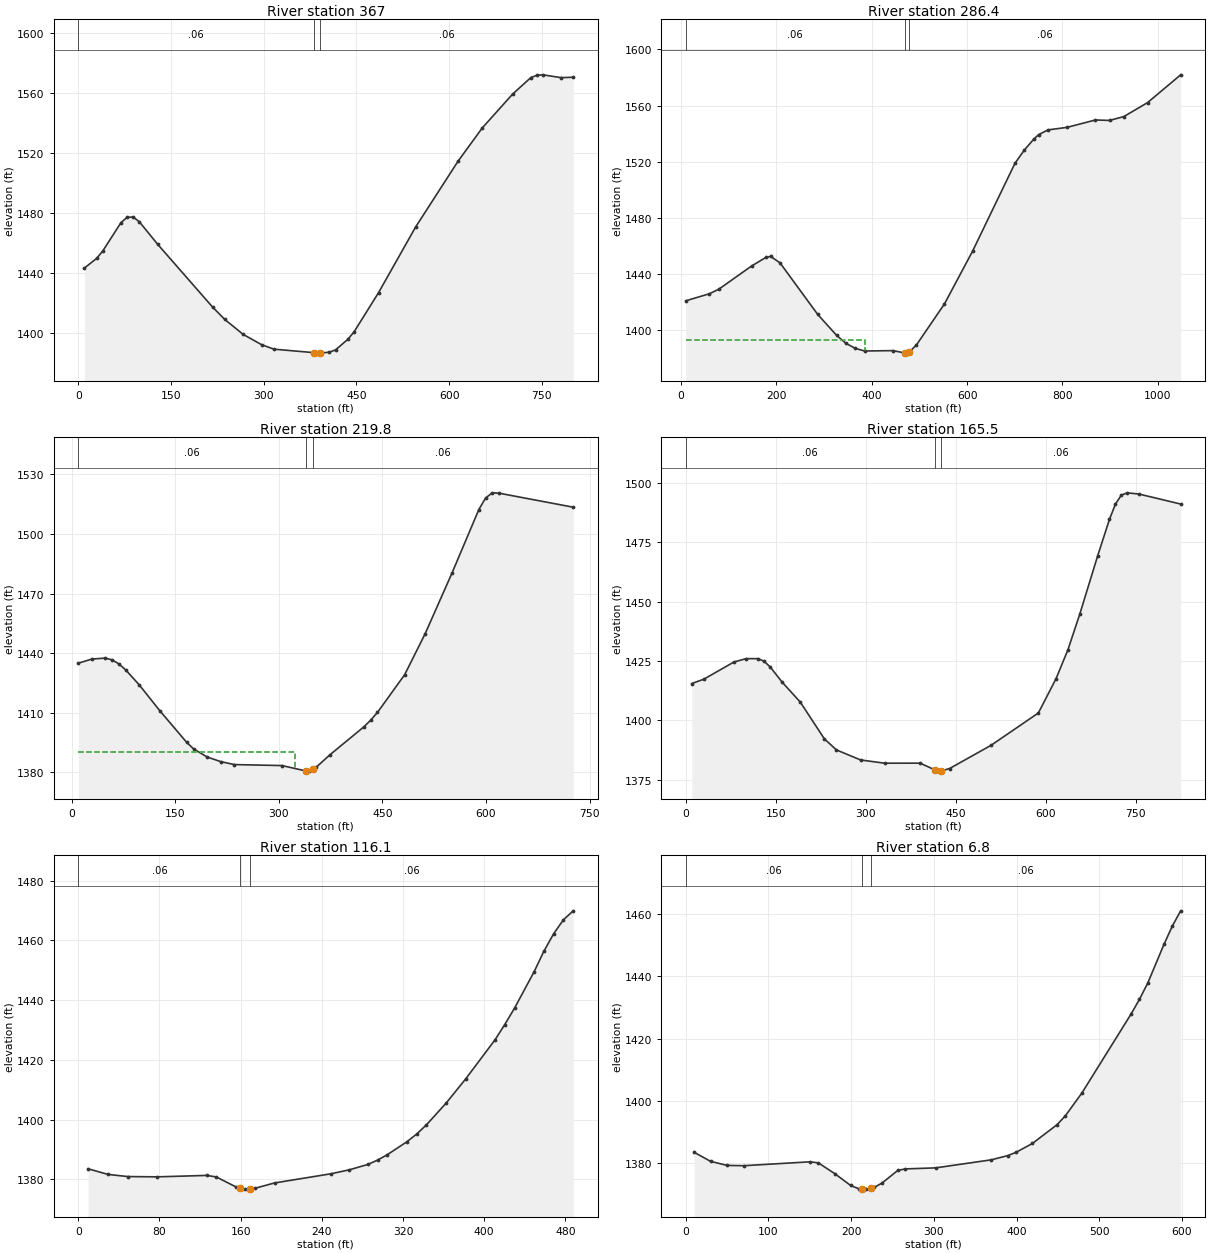
Type RM Length L Ch R = 1 ,367     ,78.2,80.5,82.9
XS GIS Cut Line= 4
     1727215.052      119615.872     1727375.316      119415.125
     1727585.565      119217.087     1727680.798      118980.494
#Sta/Elev= 30
     9.9 1443.34    29.6 1449.77    39.5 1454.67    69.2 1473.75      79 1477.21
    88.9 1477.39    98.8 1474.24   128.4 1459.22   217.4 1417.24   237.1 1409.02
   266.8 1399.04   296.7 1392.17   316.6 1389.19   381.4 1386.88   386.4 1386.56
   391.4  1386.6   406.3  1387.2   416.2 1388.71   436.1 1395.77   446.1 1400.69
   485.9 1427.01   545.7  1470.7   614.4 1514.67   653.6 1536.88   702.7 1559.47
   732.1 1570.47   741.9 1572.03   751.7 1572.33   781.1 1570.45   800.7 1570.71
#Mann= 3 , 0 , 0
       0     .06       0   381.4    .045       0   391.4     .06       0
Bank Sta=381.4,391.4
XS Rating Curve= 0 ,0
Exp/Cntr=0.3,0.1

Type RM Length L Ch R = 1 ,286.4   ,64.5,66.6,68.6
XS GIS Cut Line= 4
     1727176.185      119691.539     1727403.473      119471.438
     1727680.798      119267.679     1727737.816      118884.489
#Sta/Elev= 30
     9.9 1420.84    59.3 1425.85    79.1 1429.09   148.3 1445.73     178 1451.76
   187.9 1452.54   207.6 1447.88   286.7  1411.1   326.2 1396.24   345.9 1390.52
   365.6 1386.91   385.2 1385.05   444.2 1385.33   468.7 1383.72   473.7 1383.54
   478.7 1384.42   493.4 1389.22   552.4 1418.58   611.4 1456.19   700.3 1518.83
   720.1 1528.36     740 1536.16   749.9 1539.27   769.8 1542.69   809.5 1544.48
   869.1 1549.75   898.9 1549.44   928.7 1552.19   978.4 1562.11  1047.9 1581.94
#Mann= 3 , 0 , 0
     9.9     .06       0   468.7    .045       0   478.7     .06       0
#XS Ineff= 2 , 0
          385.41 1393.22
Permanent Ineff=
       F       F
Bank Sta=468.7,478.7
XS Rating Curve= 0 ,0
Exp/Cntr=0.3,0.1

Type RM Length L Ch R = 1 ,219.8   ,52.5,54.3,56.2
XS GIS Cut Line= 4
     1727287.964       119617.36     1727422.244      119518.366
      1727694.19      119358.447     1727792.398      119135.247
#Sta/Elev= 30
     9.8 1434.97    29.4 1437.03    49.1 1437.54    58.9 1436.62    68.7 1434.58
    78.5 1431.56    98.1 1424.02   127.6 1411.13   166.8 1395.08   176.7 1391.81
   196.4 1387.74   216.1 1385.42   235.8 1383.93   304.8 1383.44   339.3 1380.71
   344.3 1380.64   349.3 1381.63   354.1 1382.57   373.9 1388.82   423.2 1402.92
     433 1406.29   442.9 1410.18   482.3 1429.21   511.6 1449.58   550.6  1480.2
   589.6 1512.27   599.4 1518.11   609.1 1520.71   618.9 1520.53   726.2 1513.48
#Mann= 3 , 0 , 0
     9.8     .06       0   339.3    .045       0   349.3     .06       0
#XS Ineff= 2 , 0
          323.68 1390.05
Permanent Ineff=
       F       F
Bank Sta=339.3,349.3
XS Rating Curve= 0 ,0
Exp/Cntr=0.3,0.1

Type RM Length L Ch R = 1 ,165.5   ,48.5,49.4,50.4
XS GIS Cut Line= 4
     1727225.741        119682.1     1727504.197      119521.634
     1727744.896      119408.364     1727834.568      119188.903
#Sta/Elev= 30
      10 1415.51    30.1 1417.35    80.3 1424.58   100.4 1425.99   120.5 1425.99
   130.6 1424.87   140.6 1422.51   160.7 1416.06   190.8  1407.7     231 1392.19
   251.1 1387.56   291.3 1383.34   331.2 1381.98   390.4 1381.99   414.9  1379.2
   419.9 1378.64   424.9 1378.66   439.6 1379.74   508.6 1389.51   587.4 1403.11
     617 1417.62   636.8 1429.82   656.5 1444.79   686.2 1469.26   705.9 1484.65
   715.8 1491.05   725.7 1494.85   735.6  1495.8   755.3 1495.27   824.5 1491.08
#Mann= 3 , 0 , 0
       0     .06       0   414.9    .045       0   424.9     .06       0
Bank Sta=414.9,424.9
XS Rating Curve= 0 ,0
Exp/Cntr=0.3,0.1

Type RM Length L Ch R = 1 ,116.1   ,108.7,109.3,109.8
XS GIS Cut Line= 5
     1727453.133       119572.72     1727557.293      119547.424
     1727663.545      119503.486      1727714.15      119465.834
     1727837.038      119304.879
#Sta/Elev= 30
     9.7 1383.53    29.2 1381.65    48.7 1380.93      78 1380.83   126.4 1381.31
   135.9 1380.81   155.1 1377.51   159.7 1377.13   164.7 1376.72   169.7 1376.88
   174.3 1377.02   193.4 1378.79   249.2 1381.87   267.2  1383.2   285.2 1384.97
   294.9 1386.43   304.5 1388.24   323.8 1392.57   333.5 1395.17   343.1 1398.25
   362.4 1405.49   381.7  1413.6   410.6 1426.68   420.2 1431.79   429.9 1437.31
   449.2 1449.51   458.8 1456.36   468.5 1462.26   478.1  1466.9   487.7  1469.9
#Mann= 3 , 0 , 0
       0     .06       0   159.7    .045       0   169.7     .06       0
Bank Sta=159.7,169.7
XS Rating Curve= 0 ,0
Exp/Cntr=0.3,0.1

Type RM Length L Ch R = 1 ,6.8     ,8.6,6.8,4.9
XS GIS Cut Line= 5
     1727446.171      119587.226     1727607.264       119642.96
      1727679.03      119615.475     1727687.428      119533.783
     1727842.413      119313.903
#Sta/Elev= 30
      10 1383.56    30.1 1380.61    50.1 1379.32    70.2 1379.23   150.4 1380.48
   160.4 1380.12   180.1 1376.69   199.3 1372.89   208.9 1371.86   213.5 1371.79
   218.5 1371.71   223.5    1372   228.1 1372.28   237.7 1373.74   256.4 1377.73
   265.6  1378.2   302.1 1378.53   369.3 1381.11   389.2 1382.46   399.2  1383.5
   419.1 1386.36     449  1392.4     459 1395.26   478.9 1402.53   538.7 1428.02
   548.6 1432.64   558.6 1437.85   578.5 1450.44   588.5 1456.24   598.4 1461.03
#Mann= 3 , 0 , 0
       0     .06       0   213.5    .045       0   223.5     .06       0
Bank Sta=213.5,223.5
XS Rating Curve= 0 ,0
Exp/Cntr=0.3,0.1

Chan Stop Cuts=-1
Use User Specified Reach Order=0